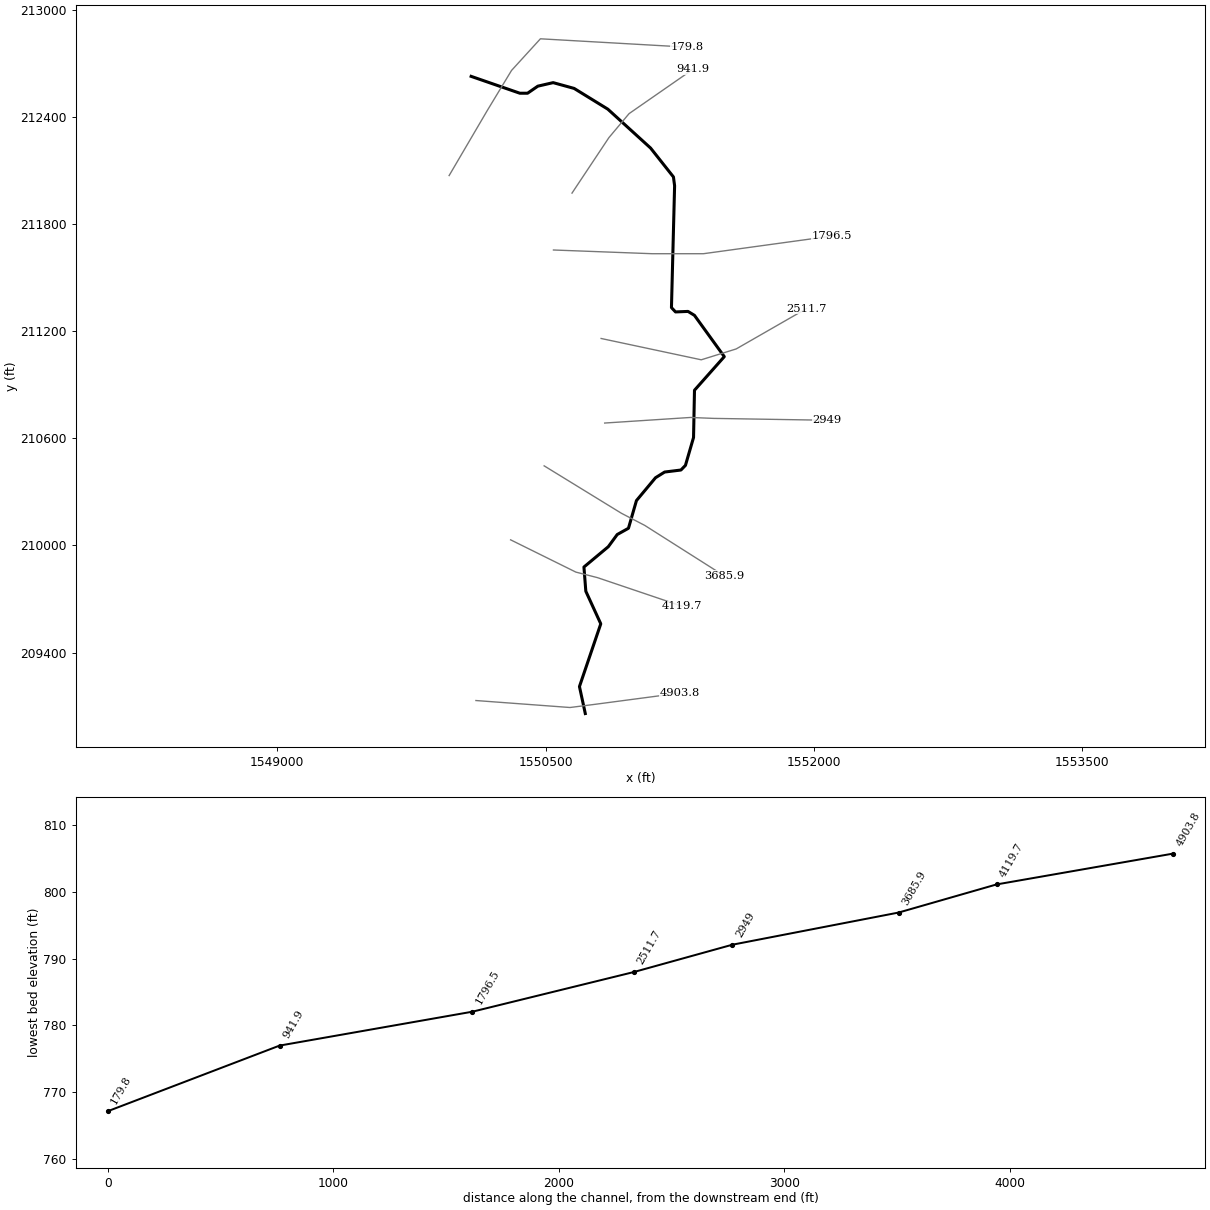
--- STRGHTFR2.prj (project) ---

Proj Title=STRGHTFR2
Current Plan=p01
Default Exp/Contr=0,0
English Units
Geom File=g01
Flow File=f01
Plan File=p01
BEGIN DESCRIPTION:
END DESCRIPTION:
DSS Export Rating Curves= 0
DSS Export Rating Curve Sorted= 0
DSS Export Volume Flow Curves= 0
DXF OffsetX= 0
DXF OffsetY= 0
DXF ScaleX= 0
DXF ScaleY= 0

--- STRGHTFR2.p01 (plan) ---

Plan Title=Floodplain
Program Version=4.00
Geom File=g01
Flow File=f01
K Sum by GR=0
Std Step Tol=0.01
Critical Tol=0.01
Num of Std Step Trials=20
Max Error Tol=0.3
Flow Tol Ratio=0.001
Split Flow NTrial=30
Split Flow Tol=0.02
Split Flow Ratio=0.02
Log Output Level=0
Friction Slope Method=1
Unsteady Friction Slope Method=2
Unsteady Bridges Friction Slope Method=1
Global Log Level=0
CheckData=False
Run HTab=0
Run UNet=0
Run PostProcess=0
UNET Theta=0
UNET Theta Warmup=0
UNET ZTol=0
UNET ZSATol=0
UNET MxIter=0
UNET MaxInSteps=0
UNET DtIC=0
UNET DtMin=0
UNET MaxCRTS=0
UNET WFStab=0
UNET SFStab=0
UNET WFX=0
UNET SFX=0
UNET DSS MLevel=0
UNET DZMax Abort=0
UNET Convert EG Bridges=0
UNET Use Existing IB Tables=0
UNET Froude Limit=0
UNET Froude Power=0
Write IC File=0
Echo Input=False
Echo Output=False
Write Detailed=0

--- STRGHTFR2.f01 (steady flow) ---

Flow Title=NFF Regression Equation
Program Version=4.10
Number of Profiles= 1
Profile Names=P100yr
River Rch & RM=STRGHTFR2,Main            ,4903.8
944.1034
River Rch & RM=STRGHTFR2,Main            ,2949
998.4843
River Rch & RM=STRGHTFR2,Main            ,179.8
1070.622
Boundary for River Rch & Prof#=STRGHTFR2,Main            , 1
Up Type= 0
Dn Type= 3
Dn Slope=0.01249
DSS Import GetInterval= 0
DSS Import GetPeak= 0
DSS Import FillOption= 0

--- STRGHTFR2.g01 (geometry) ---

Geom Title=USGS 10m DEM
Program Version=4.10

River Reach=STRGHTFR2       ,Main
Reach XY= 30
     1550721.934      209059.142     1550689.296      209210.233
     1550808.541      209561.485     1550724.933      209743.732
     1550714.395      209879.348     1550850.648      209993.203
     1550900.607      210061.389     1550963.351      210096.391
     1551008.018      210251.317     1551114.571      210379.232
     1551165.671      210411.171     1551256.817      210422.456
     1551281.991      210448.497     1551327.269      210604.549
     1551332.547      210869.061     1551499.233      211057.105
     1551332.313      211288.343     1551296.352      211310.304
     1551226.521      211307.478     1551203.781      211331.604
     1551221.369      212013.788     1551214.894      212063.113
      1551087.02      212224.893     1550848.012      212442.537
      1550659.61      212558.656     1550542.236      212591.051
     1550456.567      212571.327     1550399.178      212531.831
     1550355.775      212531.831     1550083.582      212626.225

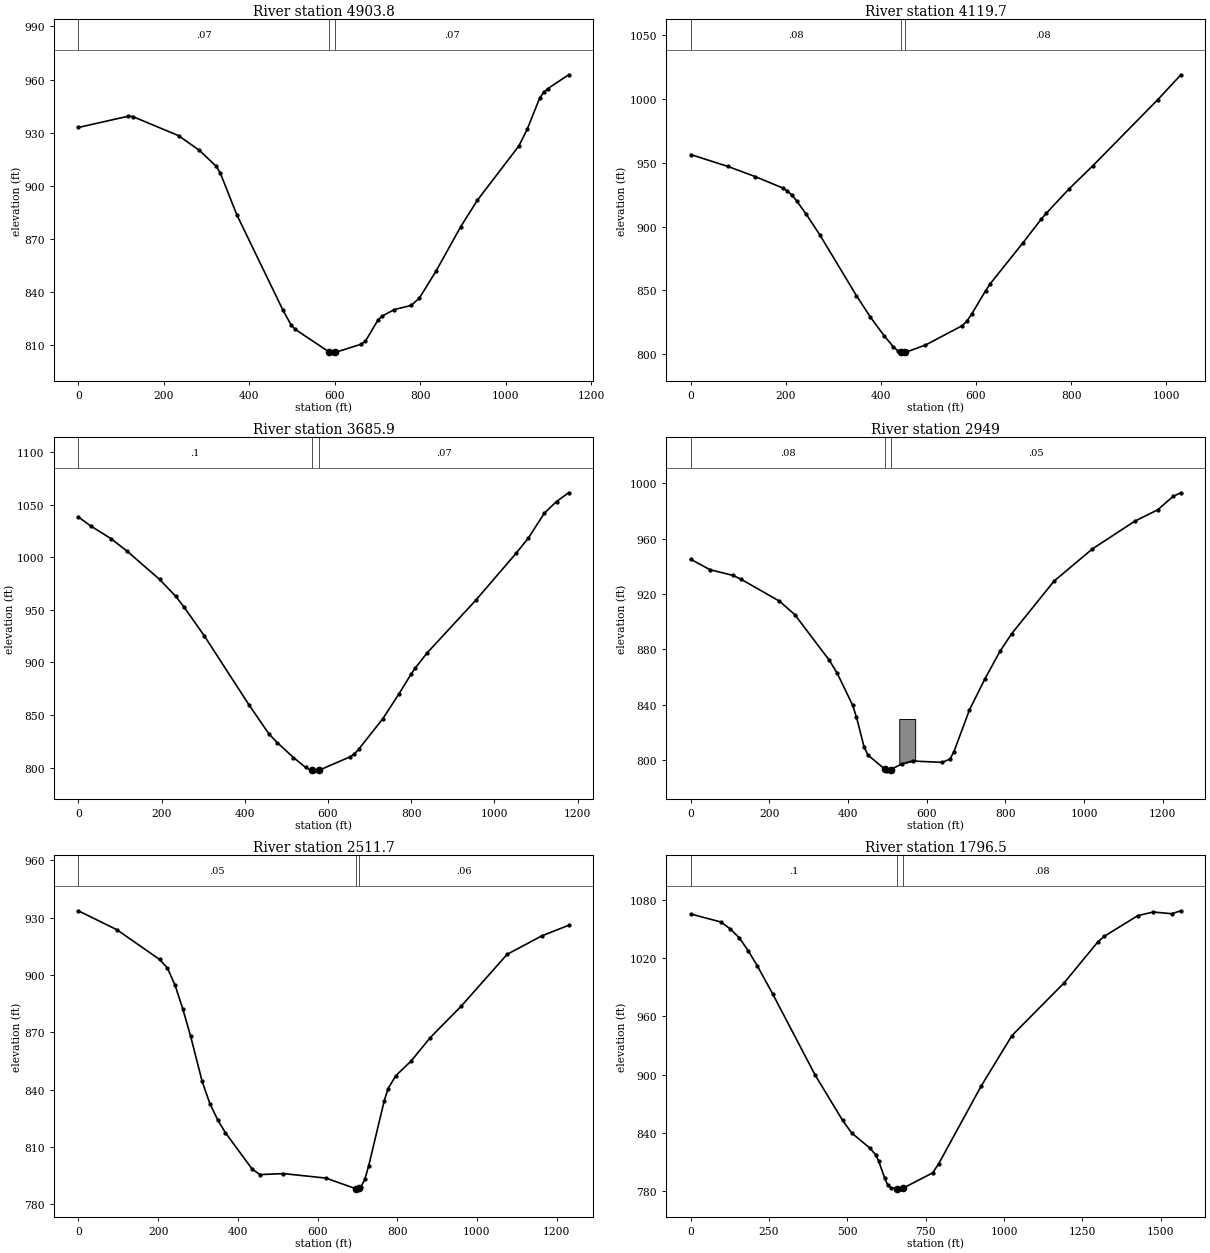
Type RM Length L Ch R = 1 ,4903.8  ,792.5,784.1,774.9
XS GIS Cut Line= 4
     1550110.329      209132.042      1550636.37      209092.979
     1550779.599      209111.208     1551250.954      209173.708
#Sta/Elev= 30
       0  932.93   117.2  939.31     127  939.11   234.4  928.33   283.3     920
   322.4  911.08   332.1  907.25   371.2  883.46   478.6  829.94   498.2  821.31
     508  818.93   586.6  806.27   594.9  805.74   601.6  806.03   662.2  810.63
   671.9  812.37     701  824.17   710.7  826.46   739.8  830.18   778.6  832.47
     798   836.6   836.8  851.74   895.1  877.02   933.9  891.88  1030.9  922.49
  1050.3  931.82  1079.4  949.35  1089.1  952.78  1098.8  954.86  1147.4  962.67
#Mann= 3 , 0 , 0
       0     .07       0   586.6    .045       0   601.6     .07       0
Bank Sta=586.6,601.6
XS Rating Curve= 0 ,0
Exp/Cntr=0.3,0.1

Type RM Length L Ch R = 1 ,4119.7  ,439.7,433.8,427.8
XS GIS Cut Line= 4
     1550304.364      210031.656     1550668.947      209851.101
     1550790.475      209819.851     1551262.697      209660.129
#Sta/Elev= 30
       0   956.5    77.5  947.24   135.6  939.24   193.7  930.25   203.4  927.97
   213.1  924.63   222.8  920.23   242.2  910.15   271.2  893.79   348.7  845.84
   377.8  829.18   406.8  814.52   426.2  805.83   435.8  802.67  441.78801.6983
   445.4  801.11  451.35801.4581   493.7  807.21   571.4  822.46   581.2  826.22
     591  831.53   620.3  849.88   630.1  855.35   698.5  887.23   737.6  906.09
   747.4  910.32   796.2  929.81   845.1  947.48     982  999.41  1030.8 1018.97
#Mann= 3 , 0 , 0
       0     .08       0  441.78    .045       0  451.35     .08       0
Bank Sta=441.78,451.35
XS Rating Curve= 0 ,0
Exp/Cntr=0.3,0.1

Type RM Length L Ch R = 1 ,3685.9  ,724.8,736.9,747.7
XS GIS Cut Line= 4
     1550491.839      210445.844     1550924.131      210180.219
     1551054.339      210112.511     1551497.047      209831.261
#Sta/Elev= 30
       0 1038.43    29.3 1030.01    78.1 1017.91   117.1 1005.94   195.2  979.07
   234.2  962.92   253.7  952.92   302.5   925.5   409.8  859.92   458.6  831.82
   478.1  823.79   517.2  809.52   546.5   800.1   560.8   797.4   566.1   796.9
  579.33797.5934   654.1  810.38   663.8  813.04   673.6  817.31   731.8  846.43
   770.7  870.09   799.8  888.84   809.5  894.52   838.7  909.24   955.2  959.13
  1052.4 1003.91  1081.5 1018.18  1120.4 1042.12  1149.5 1053.13  1178.6 1061.46
#Mann= 3 , 0 , 0
       0      .1       0   560.8    .045       0  579.33     .07       0
Bank Sta=560.8,579.33
XS Rating Curve= 0 ,0
Exp/Cntr=0.3,0.1

Type RM Length L Ch R = 1 ,2949    ,429.3,437.3,445.1
XS GIS Cut Line= 4
     1550830.381      210685.427     1551309.547      210716.677
     1551439.756      210711.469     1552075.172      210701.052
#Sta/Elev= 30
       0  945.05      49  937.51   107.8  933.34   127.4   930.7   225.4  914.81
   264.6  905.04   352.8  871.87   372.4   862.7   411.6  839.56   421.4  830.91
     441  809.15   450.8  803.42   493.1   793.4   498.8  792.08   508.1  792.89
     536  797.04     564  799.18   639.8  798.19   659.4  800.72   669.2  805.94
   708.3  835.96   747.4  858.32   786.5  878.65   815.8   891.2   923.4  929.21
  1021.1  952.54  1128.7  972.55  1187.3  980.84  1226.4  990.57    1246  993.11
#Mann= 3 , 0 , 0
       0     .08       0   493.1    .045       0   508.1     .05       0
#Block Obstruct= 1 ,-1
  530.16  570.68  829.58
Bank Sta=493.1,508.1
XS Rating Curve= 0 ,0
Exp/Cntr=0.3,0.1

Type RM Length L Ch R = 1 ,2511.7  ,721.4,715.2,707.8
XS GIS Cut Line= 4
      1550810.44      211158.826     1551370.336      211039.469
     1551565.648      211100.233     1551958.443      211325.927
#Sta/Elev= 30
       0  933.59      97  923.63   203.8  908.09   223.2  903.68   242.6  894.62
     262  882.18   281.4  868.11   310.5  844.27   329.9  832.64   349.3   824.2
   368.7  817.45   436.6  798.16     456  795.44   514.3  795.97   621.2   793.6
   695.5788.0822   699.1  787.98   703.3788.4553   708.8  789.08   718.6   792.9
   728.3  799.97   767.3  834.01     777  840.46   796.3   847.2   834.9  854.92
     883   867.2   960.2  883.57  1075.8  910.79  1162.6  920.44    1230  925.98
#Mann= 3 , 0 , 0
       0     .05       0   695.5    .045       0   703.3     .06       0
Bank Sta=695.5,703.3
XS Rating Curve= 0 ,0
Exp/Cntr=0.3,0.1

Type RM Length L Ch R = 1 ,1796.5  ,834.6,854.6,874.3
XS GIS Cut Line= 4
     1550543.922      211654.177     1551096.006      211633.344
     1551382.464      211633.344     1552101.214      211732.302
#Sta/Elev= 30
       0 1065.81    96.9 1057.52     126 1050.51   155.1 1041.26   184.2 1027.63
   213.2 1012.04   261.7  983.38   397.4  899.42   484.6  852.93   513.7  839.74
   571.6  824.21   590.7  817.06   600.2  810.59   619.3  793.05   628.9  785.95
   638.4  783.28   657.5  782.28   667.1  782.04   677.9  782.74   772.1   798.5
   791.2  807.74   927.2  888.21  1025.2  940.23  1191.9  994.75  1299.7  1037.1
  1319.4 1042.66  1427.2 1064.18  1476.2 1067.86    1535  1066.1  1564.5 1069.14
#Mann= 3 , 0 , 0
       0      .1       0   657.5    .045       0   677.9     .08       0
Bank Sta=657.5,677.9
XS Rating Curve= 0 ,0
Exp/Cntr=0.3,0.1

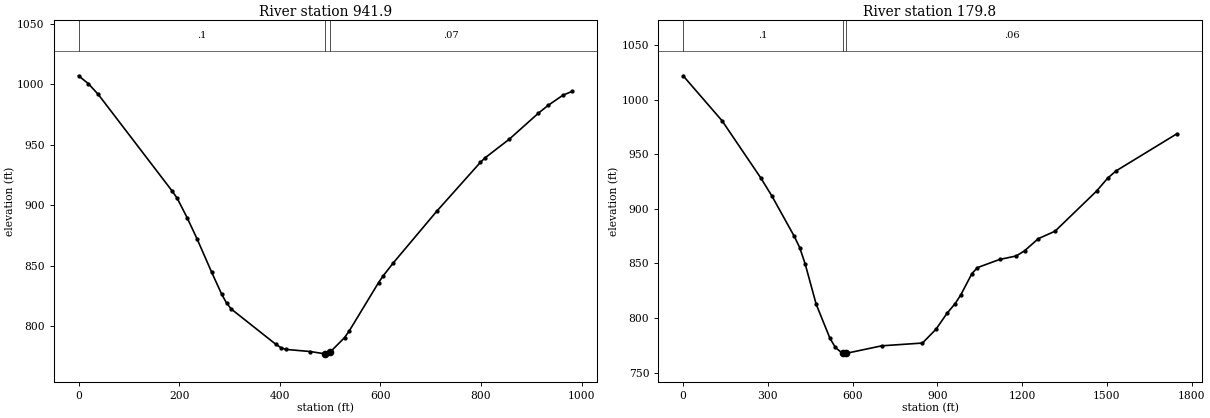
Type RM Length L Ch R = 1 ,941.9   ,758.7,762.1,765.5
XS GIS Cut Line= 4
     1550647.679      211972.629     1550853.843      212282.958
      1550966.69      212417.507     1551322.593      212664.903
#Sta/Elev= 30
       0 1007.16    19.6 1000.59    39.2  991.73   186.3  911.61   196.1  905.73
   215.7  889.77   235.3   872.4   264.7  844.42   284.3  826.51   294.1  819.05
   303.9  813.93   392.1  784.87   401.8   782.2   411.6  780.65   460.4  778.88
   489.6  776.96   499.5  778.16   528.7  790.38   538.4  796.14   596.3  835.91
     606   841.8   625.2  852.02   711.9  894.97   798.6  935.42   808.2  939.27
   856.4  954.73   914.2  976.25   933.5   982.7   962.4  990.96   981.6  994.37
#Mann= 3 , 0 , 0
       0      .1       0   489.6    .045       0   499.5     .07       0
Bank Sta=489.6,499.5
XS Rating Curve= 0 ,0
Exp/Cntr=0.3,0.1

Type RM Length L Ch R = 1 ,179.8   ,175.2,179.8,184.4
XS GIS Cut Line= 5
     1549960.589      212070.844     1550174.131      212435.427
     1550309.547      212659.386     1550471.006      212836.469
     1551293.922      212789.594
#Sta/Elev= 30
       0 1021.95   137.6  980.81   275.1  928.25   314.4  911.67     393     875
   412.7  864.49   432.2  849.31     471  812.55   519.4  781.54   538.8  772.99
   564.3767.5093   567.9  767.12   577.6  767.61   703.4  774.48   847.2  777.02
   895.1  789.68   933.7  804.13   963.1  813.25   982.8  821.12    1022  840.55
  1041.6  846.13  1120.1  853.59    1179  856.81  1208.4  861.52  1257.5  872.71
  1316.4  879.48  1463.6   916.3  1502.8  928.15  1532.2  934.72  1748.1  968.85
#Mann= 3 , 0 , 0
       0      .1       0   564.3    .045       0   577.6     .06       0
Bank Sta=564.3,577.6
XS Rating Curve= 0 ,0
Exp/Cntr=0.3,0.1

Chan Stop Cuts=-1
Use User Specified Reach Order=0
Composite Channel Slope=5